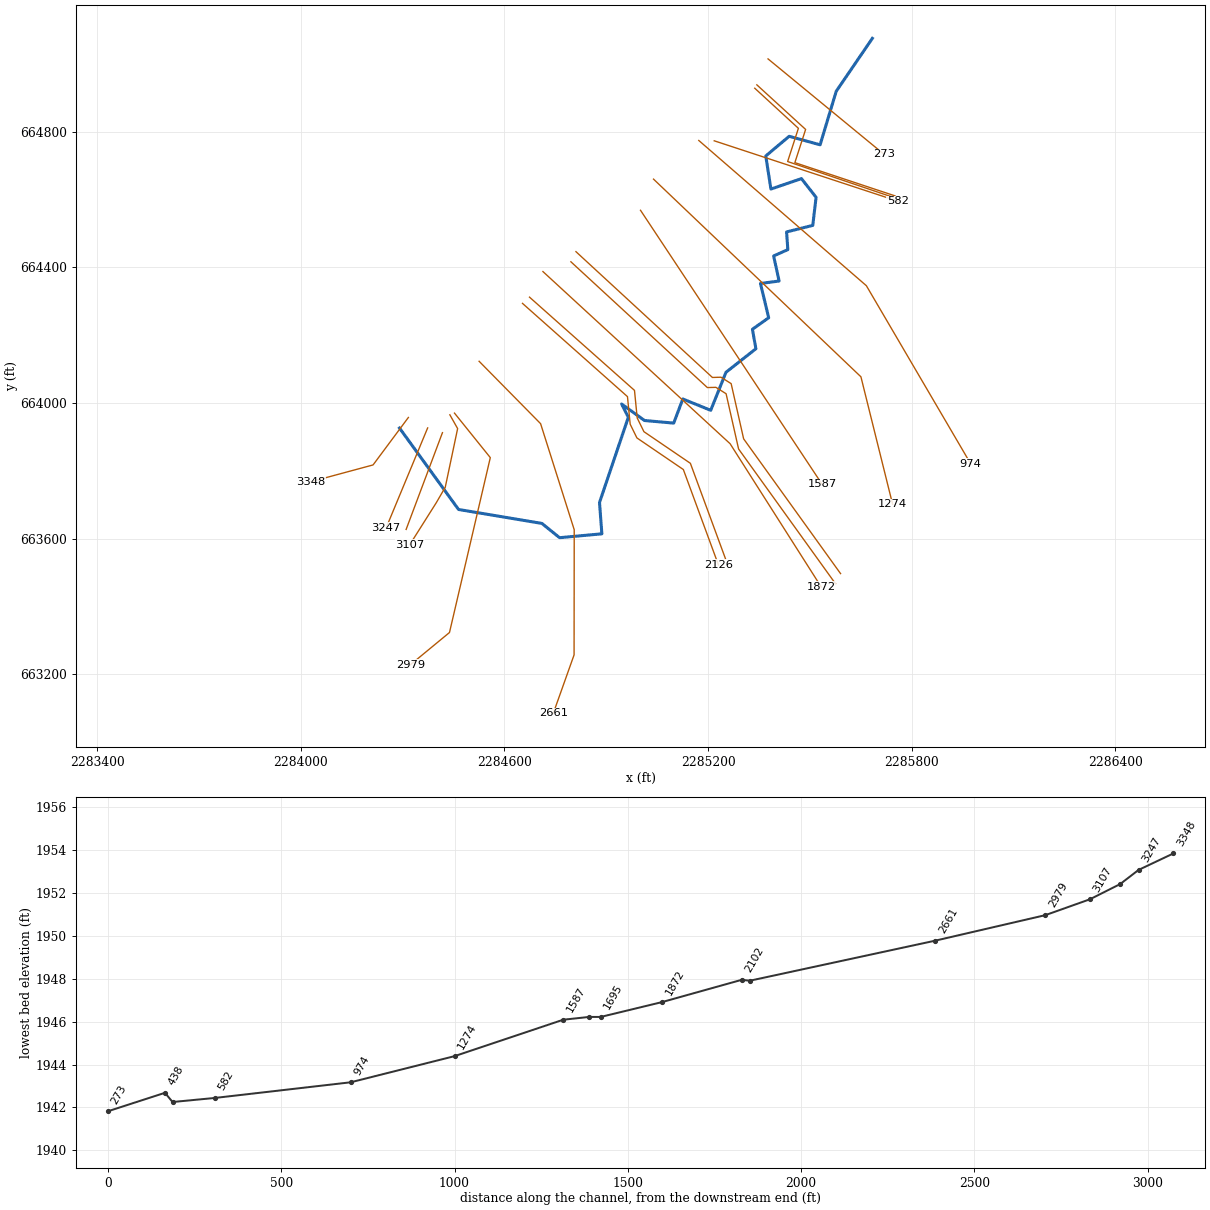
--- TROUTWNRN.prj (project) ---

Proj Title=TROUTWNRN
Current Plan=p01
Default Exp/Contr=0,0
English Units
Geom File=g01
Flow File=f01
Plan File=p01
BEGIN DESCRIPTION:
----------MODEL BY WOOD PLC 2022----------
AFH study
Randolph County, WV
HEC-RAS Version: RAS 6.2
Vertical Datum: NAVD88
Projection: NAD 1983 StatePlane West Virginia S FIPS 4702 (US Feet)
Terrain: 1-meter LIDAR (FEMA Region III 3DEP collected 2016-2018)
Land Use: 2019 NLCD
Hydrologic Method:
WV SIR2010-5033 regression equations
Additional Model Notes:
Backwater from main stem dominates to at least ~ RS 1700
END DESCRIPTION:
DSS Export Rating Curves= 0
DSS Export Rating Curve Sorted= 0
DSS Export Volume Flow Curves= 0
DXF OffsetX= 0
DXF OffsetY= 0
DXF ScaleX= 0
DXF ScaleY= 0

--- TROUTWNRN.p01 (plan) ---

Plan Title=Floodplain
Program Version=6.20
Short Identifier=Floodplain
Geom File=g01
Flow File=f01
Subcritical Flow
K Sum by GR= 0
Std Step Tol= 0.01
Critical Tol= 0.01
Num of Std Step Trials= 20
Max Error Tol= 0.3
Flow Tol Ratio= 0.001
Split Flow NTrial= 30
Split Flow Tol= 0.02
Split Flow Ratio= 0.02
Log Output Level= 0
Friction Slope Method= 1
Unsteady Friction Slope Method= 2
Unsteady Bridges Friction Slope Method= 1
Parabolic Critical Depth
Global Vel Dist= 0 , 0 , 0
Global Log Level= 0
CheckData=True
Encroach Param=-1 ,0,0, 0
Mapping Interval=1HOUR
Computation Time Step Use Courant=        0
Computation Time Step Use Time Series=    0
Computation Time Step Count To Double=0
Computation Time Step Max Doubling=0
Computation Time Step Max Halving=0
Computation Time Step Residence Courant=0
Run HTab= 0
Run UNet= 0
Run Sediment= 0
Run PostProcess= 0
Run WQNet= 0
Run RASMapper=-1
UNET Theta= 0
UNET Theta Warmup= 0
UNET ZTol= 0
UNET ZSATol= 0
UNET MxIter= 0
UNET Max Iter WO Improvement= 0
UNET MaxInSteps= 0
UNET DtIC= 0
UNET DtMin= 0
UNET MaxCRTS= 0
UNET WFStab= 0
UNET SFStab= 0
UNET WFX= 1
UNET SFX= 1
UNET Gravity=32.174
UNET 1D Methodology=Finite Difference
UNET DSS MLevel= 1
UNET Pardiso=0
UNET DZMax Abort= 0
UNET Use Existing IB Tables= 0
UNET Froude Reduction=False
UNET Froude Limit= 0
UNET Froude Power= 0
UNET D1 Cores= 0
UNET WindReference=Eulerian
UNET WindDragFormulation=Hsu (1988)
UNET D2 Coriolis=0
UNET D2 Cores= 0
UNET D2 Theta= 1
UNET D2 Theta Warmup= 1
UNET D2 Z Tol= 0.01
UNET D2 Volume Tol= 0.01
UNET D2 Max Iterations= 20
UNET D2 Equation= 0
UNET D2 RampUpFraction=0.1
UNET D2 TimeSlices= 1
UNET D2 Turbulence Formulation=Non-Conservative (original)
UNET D2 Eddy Viscosity=0.3
UNET D2 Transverse Eddy Viscosity=0.1
UNET D2 Smagorinsky Mixing=0
UNET D2 BCVolumeCheck=0
UNET D2 Cores=0
UNET D2 SolverType=PARDISO (Direct)
UNET D2 Minimum Iterations= 2147483647
UNET D2 Maximum Iterations= 2147483647
UNET D2 Restart Number= 10
UNET D2 Relaxation Coeff=1.3
UNET D2 SOR Precondition Iterations= 10
UNET D2 ILUT Maximum Fill= 8
UNET D2 ILUT Tolerance=1E-08
UNET D1D2 MaxIter= 0
UNET D1D2 ZTol=0.01
UNET D1D2 QTol=0.1
UNET D1D2 MinQTol=1
Write IC File= 0
Write IC File at Fixed DateTime=0
Write IC File at Sim End=0
Echo Input=False
Echo Parameters=False
Echo Output=False
Write Detailed= 0
HDF Write Warmup=0
HDF Write Time Slices=0
HDF Flush=0
HDF Compression= 1
HDF Chunk Size= 1
HDF Spatial Parts= 1
HDF Use Max Rows=0
HDF Fixed Rows= 1
Calibration Method= 0
Calibration Iterations= 20
Calibration Max Change=0.05
Calibration Tolerance=0.2
Calibration Maximum=1.5
Calibration Minimum=0.5
Calibration Optimization Method= 1
WQ AD Non Conservative
WQ ULTIMATE=-1
WQ Max Comp Step=1HOUR
WQ Output Interval=15MIN
WQ Output Selected Increments= 0
WQ Output face flow=0
WQ Output face velocity=0
WQ Output face area=0
WQ Output face dispersion=0
WQ Output cell volume=0
WQ Output cell surface area=0
WQ Output cell continuity=0
WQ Output cumulative cell continuity=0
WQ Output face conc=0
WQ Output face dconc_dx=0
WQ Output face courant=0
WQ Output face peclet=0
WQ Output face adv mass=0
WQ Output face disp mass=0
WQ Output cell mass=0
WQ Output cell source sink temp=0
WQ Output nsm pathways=0
WQ Output nsm derived pathways=0
WQ Create Restart=0
WQ Fixed Restart=0
WQ System Summary=0
WQ Write To DSS=0
Sorting and Armoring Iterations= 10
XS Update Threshold= 0.02
Bed Roughness Predictor= 0
Hydraulics Update Threshold= 0.02
Energy Slope Method= 1
Volume Change Method= 1
Sediment Retention Method= 0
Sediment TS Multiplier= 1
Warm Up Method= 0
XS Weighting Method= 0
Number of US Weighted Cross Sections= 1
Number of DS Weighted Cross Sections= 1
Upstream XS Weight=0
Main XS Weight=1
Downstream XS Weight=0
Number of DS XS's Weighted with US Boundary= 1
Upstream Boundary Weight= 1
Weight of XSs Associated with US Boundary= 0
Number of US XS's Weighted with DS Boundary= 1
Downstream Boundary Weight= 0.5
Weight of XSs Associated with DS Boundary= 0.5
Percentile Method= 0
Sediment Output Level= 3
Mass or Volume Output= 0
Output Increment Type= 1
Profile and TS Output Increment= 1
Transport Output Increment 1
XS Output Flag= 0
XS Output Increment= 10
Read HDF5 Sediment Hotstart= 0
Sediment Hotstart Type= 0
Write Gradation File= 0
Read Gradation Hotstart= 0
Write HDF5 File= 1
Write Binary Output= 1
Write DSS Sediment File= 0
DSS Sediment Output Type= 1
SV Curve= 0
Specific Gage Flag= 0
Subcell Erosion Methods= 0
Subcell Deposition Methods= 0
Advection Scheme= 1
Matrix Solver= 0
Implicit Weighting Factor= 1
Maximum Outer Loop Convergence Iterations= 5
Convergence Maximum Absolute= 0.001
Convergence RMSE= 0.0001
Grain Fractions Max Abs Error= 0.001
Max Subgrid Regions= 1
Max Subgrid Length Scale= 3.402823E+38
Initial Layer Thickness= 3.402823E+38
Min Layer Thickness= 3.402823E+38
Max Layer Thickness= 3.402823E+38
Number of Layers= 5

--- TROUTWNRN.f01 (steady flow) ---

Flow Title=Flow
Program Version=6.20
Number of Profiles= 1
Profile Names=P100yr
River Rch & RM=TROUTWNRN,Main,3348
     430
Boundary for River Rch & Prof#=TROUTWNRN,Main            , 1
Up Type= 0
Dn Type= 3
Dn Slope=0.00515
DSS Import GetInterval= 0
DSS Import GetPeak= 0
DSS Import FillOption= 0

--- TROUTWNRN.g01 (geometry) ---

Geom Title=Geometry
Program Version=6.20

River Reach=TROUTWNRN       ,Main
Reach XY= 30
     2284290.546      663926.0062284464.49240371663686.019229705
2284710.34398415663644.814655527     2284762.453      663602.782
     2284887.074        663614.2     2284880.129      663706.561
 2284965.0690365663957.7739784992284945.23185382663996.937561463
     2285012.768      663948.228      2285098.88      663940.589
      2285125.73      664011.654     2285207.879      663978.308
     2285252.877       664090.38     2285341.081      664159.768
     2285330.863      664217.159     2285378.812      664251.158
2285354.56148604664352.1815567052285409.51719605664359.374712465
2285393.40452715664433.3203536752285435.26869367 664452.02255865
2285431.52825267 664504.101006352285508.75208361      664523.436
2285518.50742819664606.167361836     2285475.378      664661.318
 2285385.4128682664630.5155958312285370.20802262      664728.018
2285439.18015805664786.0130396772285530.41737551664760.947870045
2285577.87409667664918.691337595     2285684.448      665074.799

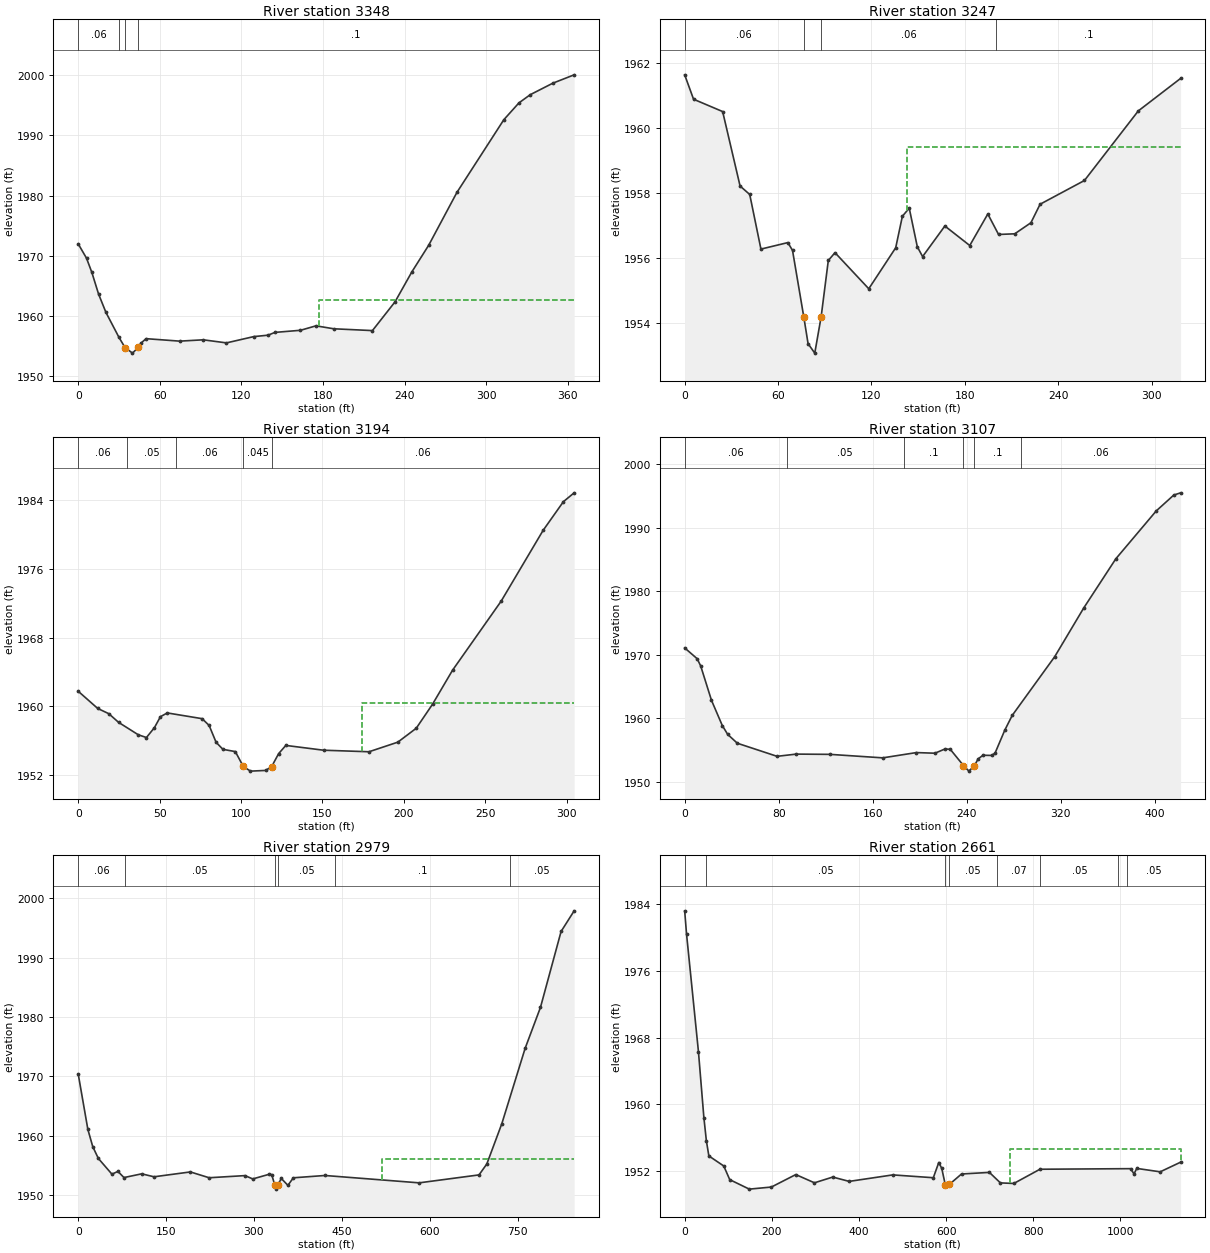
Type RM Length L Ch R = 1 ,3348    ,96.4,100.6,100.2
XS GIS Cut Line= 3
 2284316.7039779663957.2147276642284212.62098053663817.298003841
2284029.00526975663767.719722649
#Sta/Elev= 30
       0 1971.98     6.1 1969.61      10 1967.26      15 1963.63    20.4  1960.6
      30 1956.45    34.4 1954.78    39.9 1953.85   44.08 1954.79    46.1  1955.5
    49.9 1956.25    74.6 1955.84    91.9 1956.06     109 1955.55     129 1956.59
   139.6 1956.83   144.6 1957.29   163.4 1957.64   174.8 1958.38   187.9 1957.89
   216.3 1957.59   232.9 1962.36   245.3 1967.34   257.7 1971.77   278.4 1980.52
   312.9 1992.59     324 1995.38   332.3 1996.74   348.9 1998.65   364.6 2000.04
#Mann= 4, -1 ,  0
       0    0.06       0      30     0.1       0    34.4   0.045       0
   44.08     0.1       0
#XS Ineff= 2 , 0
                          177.28         1962.66
Permanent Ineff=
       F       F
Bank Sta=34.4,44.08
XS Rating Curve= 0 ,0
Exp/Cntr(USF)=0,0
Exp/Cntr=0.3,0.1

Type RM Length L Ch R = 1 ,3247    ,53.4,53.1,57
XS GIS Cut Line= 2
2284373.52081507663926.407726691 2284251.2721357663632.035139825
#Sta/Elev= 30
       0 1961.64     5.7 1960.89    24.4 1960.51    35.6 1958.22    41.8 1957.96
      49 1956.28    66.3 1956.48    69.3 1956.24   76.59 1954.18    79.3 1953.37
    83.6 1953.08    87.7  1954.2    92.3 1955.93    96.6 1956.17   118.3 1955.06
   135.6 1956.32   139.9 1957.29   144.3 1957.54   149.5 1956.35   152.9 1956.05
   167.2 1956.99   183.2 1956.39   194.8 1957.36   201.7 1956.73   212.1 1956.75
   222.5 1957.09   228.4 1957.66   256.9 1958.39   291.5 1960.53   318.7 1961.53
#Mann= 4, -1 ,  0
       0    0.06       0   76.59   0.045       0    87.7    0.06       0
     200     0.1       0
#XS Ineff= 2 , 0
                          142.85         1959.42
Permanent Ineff=
       F       F
Bank Sta=76.59,87.7
XS Rating Curve= 0 ,0
Exp/Cntr(USF)=0,0
Exp/Cntr=0.3,0.1

Type RM Length L Ch R = 1 ,3194    ,90.1,87.3,81.7
XS GIS Cut Line= 2
2284417.13989267663912.4359908952284310.09312326663627.220583552
#Sta/Elev= 30
       0 1961.74      12 1959.73    18.8 1959.12    24.8 1958.11    36.9 1956.66
    41.9 1956.34    46.8 1957.49    50.5 1958.77    54.7 1959.21    76.1 1958.54
    80.4 1957.75    84.7 1955.78    88.9 1954.96    96.5  1954.7   101.4 1952.96
   105.8 1952.42   115.1  1952.5   118.8 1952.95   123.1 1954.46   127.5 1955.42
   150.7 1954.86   178.6 1954.68   196.3  1955.8   207.6 1957.42   217.6 1960.22
   229.9 1964.19   259.8 1972.26   285.5  1980.5     298 1983.86   304.6 1984.89
#Mann= 5, -1 ,  0
       0    0.06       0      30    0.05       0      60    0.06       0
   101.4   0.045       0   118.8    0.06       0
#XS Ineff= 2 , 0
                          174.51         1960.33
Permanent Ineff=
       F       F
Bank Sta=101.4,118.8
XS Rating Curve= 0 ,0
Exp/Cntr(USF)=0,0
Exp/Cntr=0.3,0.1

Type RM Length L Ch R = 1 ,3107    ,127,128.5,128.4
XS GIS Cut Line= 5
2284438.97409002663965.0438363572284461.88118403663924.419484949
2284425.41916939663751.512516759 2284399.1105217663706.146807366
2284321.11489649663582.634918463
#Sta/Elev= 30
       0 1971.11    10.6 1969.41    13.6 1968.28    22.8 1962.86      32 1958.89
    36.6 1957.49    44.8  1956.1    78.6 1954.04    94.9 1954.39   123.5 1954.35
   168.5  1953.8   197.1 1954.63   212.9 1954.53   221.6 1955.21     226 1955.13
  237.17 1952.59   241.8 1951.71   246.5 1952.58   249.7 1953.65   253.8 1954.21
   261.1 1954.18     264 1954.53   272.3 1958.15   278.6 1960.47   314.8 1969.73
   339.5  1977.4   366.8 1985.14   401.2 1992.68   416.1 1995.17   421.9 1995.52
#Mann= 6, -1 ,  0
       0    0.06       0   86.64    0.05       0  186.64     0.1       0
  237.17   0.045       0   246.5     0.1       0  285.79    0.06       0
Bank Sta=237.17,246.5
XS Rating Curve= 0 ,0
Exp/Cntr(USF)=0,0
Exp/Cntr=0.3,0.1

Type RM Length L Ch R = 1 ,2979    ,313.9,317.6,316.7
XS GIS Cut Line= 4
2284452.62491873663970.0213998932284558.21137582663838.814699534
2284437.87386957663323.3043501942284322.97096038663228.587087213
#Sta/Elev= 30
       0 1970.38    16.5 1961.03    24.8 1958.14    34.4 1956.14    57.6 1953.49
    67.8 1953.96    78.1 1952.92   108.4 1953.55   129.4 1953.05   191.5 1953.87
   223.5 1952.89   284.7 1953.25     298 1952.69   326.2 1953.48   330.3 1953.42
  335.42 1951.73   338.5 1950.97   341.3 1951.74   346.7 1952.77     358 1951.61
   367.3 1952.88   421.2 1953.27   582.1 1952.03   684.3 1953.37   697.6 1955.21
   723.2    1962     763 1974.71   789.2 1981.62   824.4 1994.42   846.7  1997.9
#Mann= 6, -1 ,  0
       0    0.06       0      80    0.05       0  335.42   0.045       0
   341.3    0.05       0  438.42     0.1       0  737.78    0.05       0
#XS Ineff= 2 , 0
                          519.04         1956.02
Permanent Ineff=
       F       F
Bank Sta=335.42,341.3
XS Rating Curve= 0 ,0
Exp/Cntr(USF)=0,0
Exp/Cntr=0.3,0.1

Type RM Length L Ch R = 1 ,2661    ,530.4,535.3,533.6
XS GIS Cut Line= 5
2284525.19408929664122.8328811912284706.45020987663938.911622307
2284805.57056482663626.2025298562284805.14300723663257.296337356
2284743.79010488663084.923185352
#Sta/Elev= 30
       0 1983.23     4.2 1980.48    31.6  1966.3    44.1 1958.35    49.8 1955.58
    55.5 1953.77    89.7 1952.56   103.4 1950.92   148.3 1949.78   198.9 1950.03
     255 1951.53   297.8 1950.54   339.8 1951.23   377.5 1950.71   477.6 1951.49
   570.6 1951.15   583.1 1952.98   589.9 1952.28  598.03 1950.32   607.3 1950.34
   635.3  1951.6   699.3 1951.79   724.5 1950.53   755.3 1950.46   815.3 1952.17
  1023.2 1952.24  1031.2 1951.61  1037.4 1952.27  1091.2 1951.86  1138.1 1953.02
#Mann= 8, -1 ,  0
       0    0.06       0      50    0.05       0  598.03   0.045       0
   607.3    0.05       0  716.27    0.07       0  816.27    0.05       0
  995.18    0.07       0 1015.18    0.05       0
#XS Ineff= 2 , 0
                          746.44          1954.6
Permanent Ineff=
       F       F
Bank Sta=598.03,607.3
XS Rating Curve= 0 ,0
Exp/Cntr(USF)=0,0
Exp/Cntr=0.3,0.1

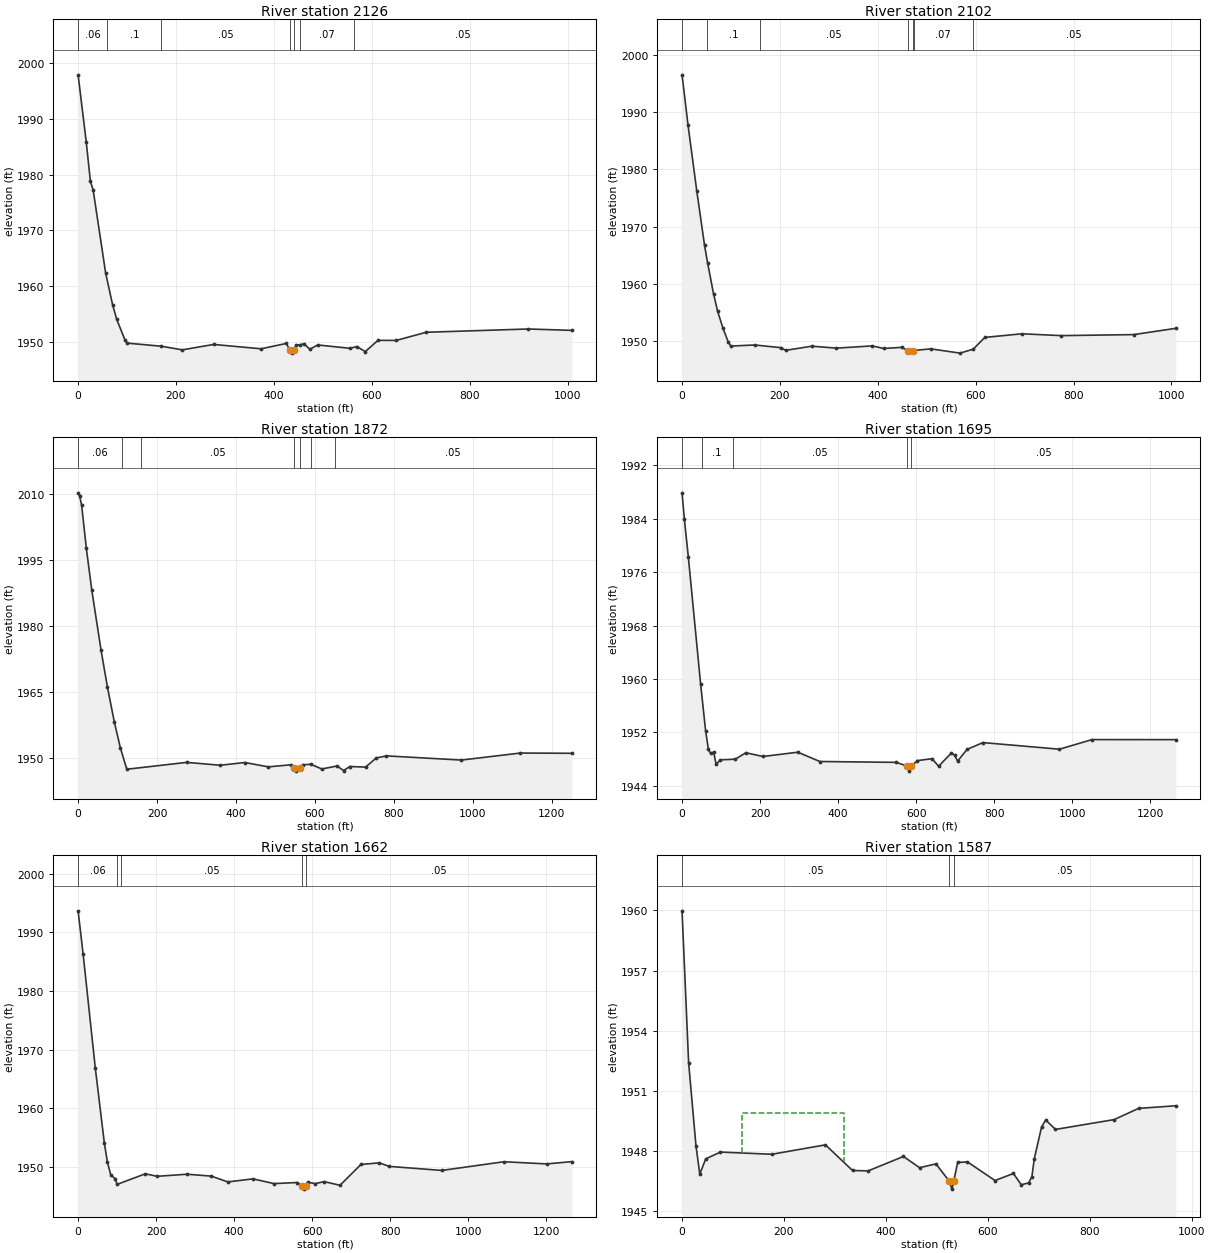
Type RM Length L Ch R = 1 ,2126    ,24.2,23.8,25.7
XS GIS Cut Line= 6
2284653.08149261 664293.484588562284962.55122105664018.643157434
2284970.52724129663937.338959191 2284990.3472201663896.915851235
2285127.28525647663803.683824071 2285230.7547096663522.344921518
#Sta/Elev= 30
       0 1997.94    16.6 1985.91    25.1 1978.83    30.9 1977.16    56.2 1962.35
    70.4 1956.63      79 1953.96    95.9 1950.25   100.4 1949.71     170 1949.15
   212.8  1948.5     277 1949.47   373.9 1948.69   425.5 1949.65  432.35 1948.48
   437.5 1947.91   440.6 1948.49   445.5 1949.36   453.5  1949.4   461.5  1949.6
   473.5  1948.6   489.5 1949.38   556.4 1948.77   568.9  1949.1   586.9  1948.2
   612.7 1950.21   649.7 1950.19   711.4 1951.66     920 1952.25  1008.6    1952
#Mann= 7, -1 ,  0
       0    0.06       0      60     0.1       0     170    0.05       0
  432.35   0.045       0   440.6    0.05       0   453.5    0.07       0
  562.73    0.05       0
Bank Sta=432.35,440.6
XS Rating Curve= 0 ,0
Exp/Cntr(USF)=0,0
Exp/Cntr=0.3,0.1

Type RM Length L Ch R = 1 ,2102    ,220.3,230.3,231
XS GIS Cut Line= 6
2284673.77107803 664311.866448192284983.24080647664037.025017064
2284991.21682671663955.7208188222285011.03680553663915.297710865
 2285147.9748419663822.0656837012285251.44429503663540.726781148
#Sta/Elev= 30
       0 1996.46    12.1 1987.77      30 1976.28      46 1966.72    52.2 1963.69
    64.3 1958.31    72.8 1955.21    83.5 1952.32    94.3 1949.91    99.5 1949.18
   148.6 1949.37   201.2 1948.91   211.9 1948.44   265.4 1949.16   315.3 1948.82
   388.9 1949.21   411.6 1948.76   449.7 1948.96  460.63 1948.35   463.9 1948.06
   471.9 1948.35   473.5 1948.42   508.5 1948.69   568.1 1947.95   594.9 1948.64
   618.6 1950.69   694.5 1951.32   775.1    1951   922.9 1951.18  1008.6 1952.27
#Mann= 7, -1 ,  0
       0    0.06       0      50     0.1       0     160    0.05       0
  460.63   0.045       0   471.9    0.05       0   473.5    0.07       0
  593.95    0.05       0
Bank Sta=460.63,471.9
XS Rating Curve= 0 ,0
Exp/Cntr(USF)=0,0
Exp/Cntr=0.3,0.1

Type RM Length L Ch R = 1 ,1872    ,178.2,176.3,178
XS GIS Cut Line= 3
2284713.37778513664387.2432330022285265.10347164663879.764310779
2285533.91789396663457.279186046
#Sta/Elev= 30
       0 2010.28     3.8 2009.63       9 2007.42    20.8  1997.7    34.6 1988.16
    58.1 1974.48    74.2 1966.09    91.7 1958.12   107.1  1952.2   123.4 1947.34
   274.8  1948.9   360.1 1948.25   422.6 1948.87   481.9 1947.88   538.5 1948.35
  546.15 1947.52   552.6 1946.91   561.1 1947.52     569 1948.35   589.4 1948.47
   617.5  1947.4     656 1948.08   672.3 1947.05   688.4 1947.96   728.1 1947.83
   755.3 1949.91   781.1 1950.38     971 1949.43  1120.5 1951.03  1250.4 1950.97
#Mann= 7, -1 ,  0
       0    0.06       0     110     0.1       0     160    0.05       0
  546.15   0.045       0   561.1    0.05       0     590    0.07       0
     650    0.05       0
Bank Sta=546.15,561.1
XS Rating Curve= 0 ,0
Exp/Cntr(USF)=0,0
Exp/Cntr=0.3,0.1

Type RM Length L Ch R = 1 ,1695    ,33.6,33.6,33.7
XS GIS Cut Line= 6
2284795.73553323664416.1584153492285198.02922261664045.321154958
2285223.19838464664046.0321321852285253.24394265664027.166316689
 2285290.0792858663864.3125993472285575.73677486663467.151339163
#Sta/Elev= 30
       0 1987.86       6 1983.88    16.2 1978.21    47.7  1959.2    60.4 1952.27
    67.5 1949.53    73.2 1948.86    81.1 1949.06    87.3 1947.24    98.5 1947.91
   136.6 1948.01   163.7 1948.97   207.3 1948.41   296.8 1949.05   353.4 1947.66
   549.3 1947.53   577.21946.968   582.4 1946.22     5881946.954   603.2 1947.79
   640.8 1948.08   657.9 1946.96   690.1 1948.89   698.9 1948.64   706.3 1947.71
   730.8 1949.47   771.5 1950.49   967.6  1949.5  1051.3 1950.94  1265.7 1950.93
#Mann= 5, -1 ,  0
       0    0.06       0      50     0.1       0     130    0.05       0
   577.2   0.045       0     588    0.05       0
Bank Sta=577.2,588
XS Rating Curve= 0 ,0
Exp/Cntr(USF)=0,0
Exp/Cntr=0.3,0.1

Type RM Length L Ch R = 1 ,1662    ,76.5,74.5,71.7
XS GIS Cut Line= 6
2284810.63560506664445.9663229452285212.92929444664075.129062554
2285238.09845647664075.8400397812285268.14401449664056.974224285
2285304.97935763663894.1205069432285590.63684669663496.959246759
#Sta/Elev= 30
       0 1993.68      13 1986.25    44.1 1966.87    67.4 1954.02    75.2 1950.82
    83.7 1948.66    94.6    1948     100 1947.03   172.3 1948.83   202.6 1948.41
   279.5 1948.76   341.3 1948.44   383.8 1947.45   448.2 1947.97   502.6 1947.16
   562.5 1947.35   573.51946.717   579.2 1946.22   583.2 1946.73   588.2  1947.4
   608.1 1947.16   630.8  1947.5   671.5 1946.88   725.3 1950.43   772.2  1950.7
   797.3  1950.1   932.6 1949.41  1091.8 1950.89  1201.4 1950.52  1265.7 1950.91
#Mann= 5, -1 ,  0
       0    0.06       0     100     0.1       0     110    0.05       0
   573.5   0.045       0   583.2    0.05       0
Bank Sta=573.5,583.2
XS Rating Curve= 0 ,0
Exp/Cntr(USF)=0,0
Exp/Cntr=0.3,0.1

Type RM Length L Ch R = 1 ,1587    ,310,313.8,308.8
XS GIS Cut Line= 2
2285000.94742628664567.9679259592285536.09446715663760.497538853
#Sta/Elev= 30
       0 1959.98    12.9  1952.4    27.3 1948.26    34.8 1946.84    46.5  1947.6
    75.3 1947.94   176.1 1947.83   281.4  1948.3   334.5 1947.02   365.1    1947
   434.4 1947.72   466.1 1947.16   498.2 1947.35  523.921946.502   529.6 1946.09
  533.231946.496   540.8 1947.42     560 1947.45   614.1 1946.52   650.3 1946.87
   665.6 1946.31     680  1946.4   686.5 1946.71   691.2 1947.61   705.6  1949.2
   713.6 1949.54   732.8 1949.07   847.9 1949.56   895.9 1950.12   968.7 1950.25
#Mann= 3, -1 ,  0
       0    0.05       0  523.92   0.045       0  533.23    0.05       0
#XS Ineff= 1 ,-1
  118.13  317.561949.899
Permanent Ineff=
       T
Bank Sta=523.92,533.23
XS Rating Curve= 0 ,0
Exp/Cntr(USF)=0,0
Exp/Cntr=0.3,0.1

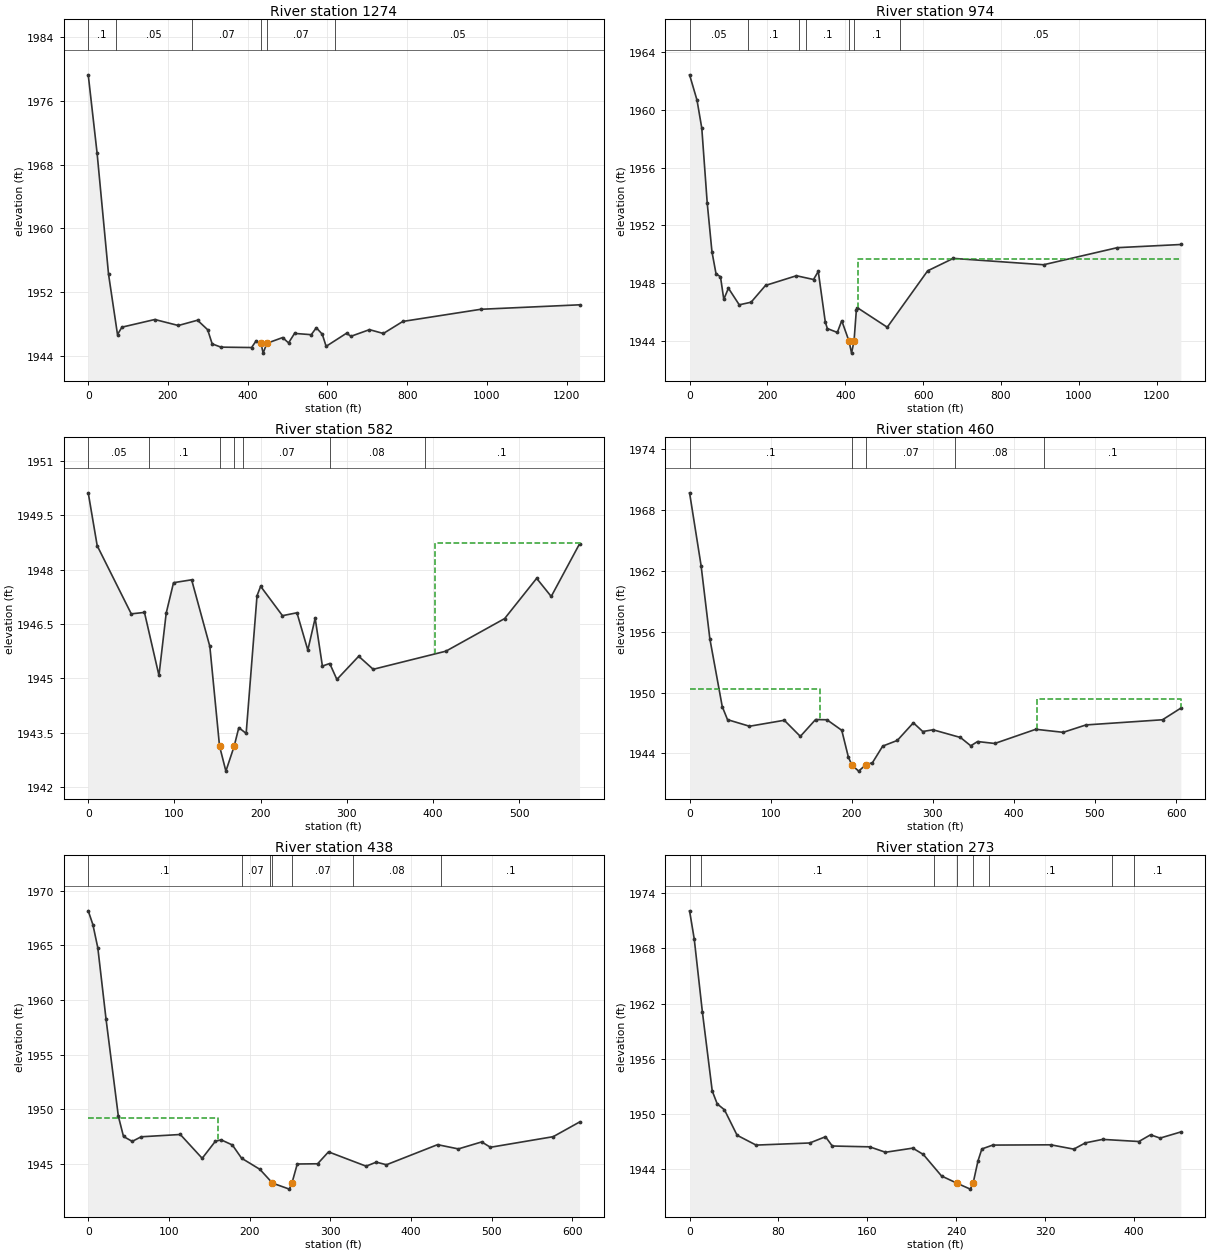
Type RM Length L Ch R = 1 ,1274    ,292.4,299.8,293
XS GIS Cut Line= 3
2285039.33512232 664659.807641322285650.72006601664077.041909635
2285744.14107933663701.136867242
#Sta/Elev= 30
       0 1979.24    22.3  1969.4    50.9 1954.28    73.4 1946.72    84.5 1947.64
   166.9  1948.6     226 1947.85   274.1 1948.51   299.5 1947.32   310.8 1945.55
   332.7 1945.14   409.6 1945.09   421.2 1945.94  433.28 1945.61   438.6 1944.39
   447.9 1945.62   487.5 1946.34   502.4 1945.67   517.4 1946.86   559.3  1946.7
     572 1947.57   586.9 1946.76   596.6 1945.24   647.7 1946.88   658.9  1946.5
   705.3 1947.33   740.1 1946.85     789 1948.36   984.4 1949.88    1232 1950.44
#Mann= 6, -1 ,  0
       0     0.1       0      70    0.05       0     260    0.07       0
  433.28   0.045       0   447.9    0.07       0     620    0.05       0
Bank Sta=433.28,447.9
XS Rating Curve= 0 ,0
Exp/Cntr(USF)=0,0
Exp/Cntr=0.3,0.1

Type RM Length L Ch R = 1 ,974     ,387.4,391.8,386.1
XS GIS Cut Line= 3
2285172.75087105664773.7197034872285666.78761795664345.561578008
2285974.23053714663820.734776569
#Sta/Elev= 30
       0 1962.41    19.1 1960.66    31.4 1958.72    45.3 1953.56    57.5 1950.18
      68 1948.65    79.4 1948.45    87.9 1946.89    99.8 1947.66   127.6 1946.51
     158 1946.69   195.1 1947.85   274.5 1948.52   318.4 1948.26   330.6 1948.82
   348.6 1945.33   353.9 1944.87   379.5  1944.6   390.9 1945.41  409.66 1943.99
   416.1 1943.17   422.5 1944.01   428.4 1946.14     431 1946.31   507.8 1944.96
   611.6 1948.86   677.4 1949.72   909.4 1949.28  1098.6 1950.46    1262 1950.68
#Mann= 7, -1 ,  0
       0    0.05       0     150     0.1       0     280    0.07       0
     300     0.1       0  409.66   0.045       0   422.5     0.1       0
     540    0.05       0
#XS Ineff= 2 , 0
                          433.22         1949.71
Permanent Ineff=
       F       F
Bank Sta=409.66,422.5
XS Rating Curve= 0 ,0
Exp/Cntr(USF)=0,0
Exp/Cntr=0.3,0.1

Type RM Length L Ch R = 1 ,582     ,130.7,122.1,102.4
XS GIS Cut Line= 2
2285218.27079787664772.7589103022285759.39541437664594.780217754
#Sta/Elev= 30
       0 1950.12    10.4 1948.66    49.9 1946.78    65.2 1946.82      82 1945.08
    90.4  1946.8    98.9 1947.64   119.9 1947.72     141 1945.88  152.211943.135
   159.6 1942.44   169.1 1943.12   174.6 1943.64   183.1 1943.48   195.7 1947.28
   199.9 1947.54   225.2 1946.73     242 1946.81   254.6 1945.78   263.1 1946.66
   271.5 1945.34     280 1945.41   288.3 1944.97   313.6 1945.61   330.4 1945.25
   414.7 1945.75   482.8 1946.65   519.9 1947.76   536.8 1947.26   569.6 1948.71
#Mann= 7, -1 ,  0
       0    0.05       0      70     0.1       0  152.21   0.045       0
   169.1     0.1       0     180    0.07       0     280    0.08       0
     390     0.1       0
#XS Ineff= 2 , 0
                          402.11        1948.737
Permanent Ineff=
       F       T
Bank Sta=152.21,169.1
XS Rating Curve= 0 ,0
Exp/Cntr(USF)=0,0
Exp/Cntr=0.3,0.1

Type RM Length L Ch R = 1 ,460     ,21.8,21.9,24.3
XS GIS Cut Line= 4
2285337.73589299664927.7411655172285466.40573363664809.557197814
2285434.68295032664711.6516981982285745.55833164664606.157886021
#Sta/Elev= 30
       0 1969.72    14.2 1962.54      25 1955.32    40.3 1948.62    46.8 1947.33
    73.9 1946.68   116.8 1947.27   136.6 1945.68   155.4 1947.34   169.4 1947.32
   187.7 1946.28   195.8 1943.65  200.09 1942.86   208.5 1942.25   217.2 1942.86
   225.6 1943.09   238.2 1944.72   256.2 1945.28     276 1947.02   287.6 1946.16
   300.3 1946.33   334.1 1945.57   346.8 1944.75   355.2 1945.17   376.4 1944.98
     427 1946.38   460.8 1946.08   488.9 1946.81   583.3 1947.32   605.9 1948.47
#Mann= 5, -1 ,  0
       0     0.1       0  200.09   0.045       0   217.2    0.07       0
  327.63    0.08       0  437.63     0.1       0
#XS Ineff= 2 , 0
          161.05 1950.33  428.15         1949.38
Permanent Ineff=
       F       F
Bank Sta=200.09,217.2
XS Rating Curve= 0 ,0
Exp/Cntr(USF)=0,0
Exp/Cntr=0.3,0.1

Type RM Length L Ch R = 1 ,438     ,152.8,164.4,180.7
XS GIS Cut Line= 4
2285343.92523813664937.6728810312285487.68773116664806.282842482
2285455.96494785664708.3773428652285751.11881626664610.429856887
#Sta/Elev= 30
       0 1968.15     5.8 1966.88    11.9 1964.75      22 1958.28    37.3 1949.36
    43.7  1947.5    54.5 1947.05    65.6 1947.47   114.1 1947.68   141.2  1945.5
   157.5 1947.06   164.7 1947.19   178.6 1946.72     190 1945.51   212.7 1944.49
   228.3 1943.23   249.2 1942.68  252.39 1943.23     259 1944.98   284.2    1945
   297.7 1946.09   344.3 1944.78   356.9 1945.15   369.5 1944.91   432.8 1946.75
   458.6 1946.36   487.5    1947   498.3 1946.51   576.1 1947.48   608.7 1948.82
#Mann= 7, -1 ,  0
       0     0.1       0     190    0.07       0  224.76     0.1       0
   228.3   0.045       0  252.39    0.07       0  327.68    0.08       0
  437.68     0.1       0
#XS Ineff= 2 , 0
          160.52 1949.22
Permanent Ineff=
       F       F
Bank Sta=228.3,252.39
XS Rating Curve= 0 ,0
Exp/Cntr(USF)=0,0
Exp/Cntr=0.3,0.1

Type RM Length L Ch R = 1 ,273     ,,,
XS GIS Cut Line= 2
2285376.91623631665014.1665872312285718.57406044664733.160913921
#Sta/Elev= 30
       0 1972.09     4.2 1969.03    11.5 1961.13    20.4  1952.5    24.9 1951.09
    31.4 1950.45    42.8 1947.68    59.9 1946.61   108.2 1946.84   122.4 1947.52
   128.5 1946.51   162.2 1946.42   176.4 1945.83     201 1946.28   210.5 1945.59
   226.9 1943.25     241 1942.45   252.8 1941.82  255.28 1942.44   259.7 1944.88
   263.2 1946.19     273 1946.61   325.3 1946.64     346 1946.17   356.4 1946.85
   371.9 1947.23   404.6    1947   415.1 1947.73   423.7 1947.37   442.4 1948.04
#Mann= 8, -1 ,  0
       0    0.05       0      10     0.1       0     220    0.07       0
     241   0.045       0  255.28    0.07       0     270     0.1       0
     380    0.07       0     400     0.1       0
Bank Sta=241,255.28
XS Rating Curve= 0 ,0
Exp/Cntr(USF)=0,0
Exp/Cntr=0.3,0.1
LCMann Table=0

Chan Stop Cuts=-1
Use User Specified Reach Order=0
Composite Channel Slope=5